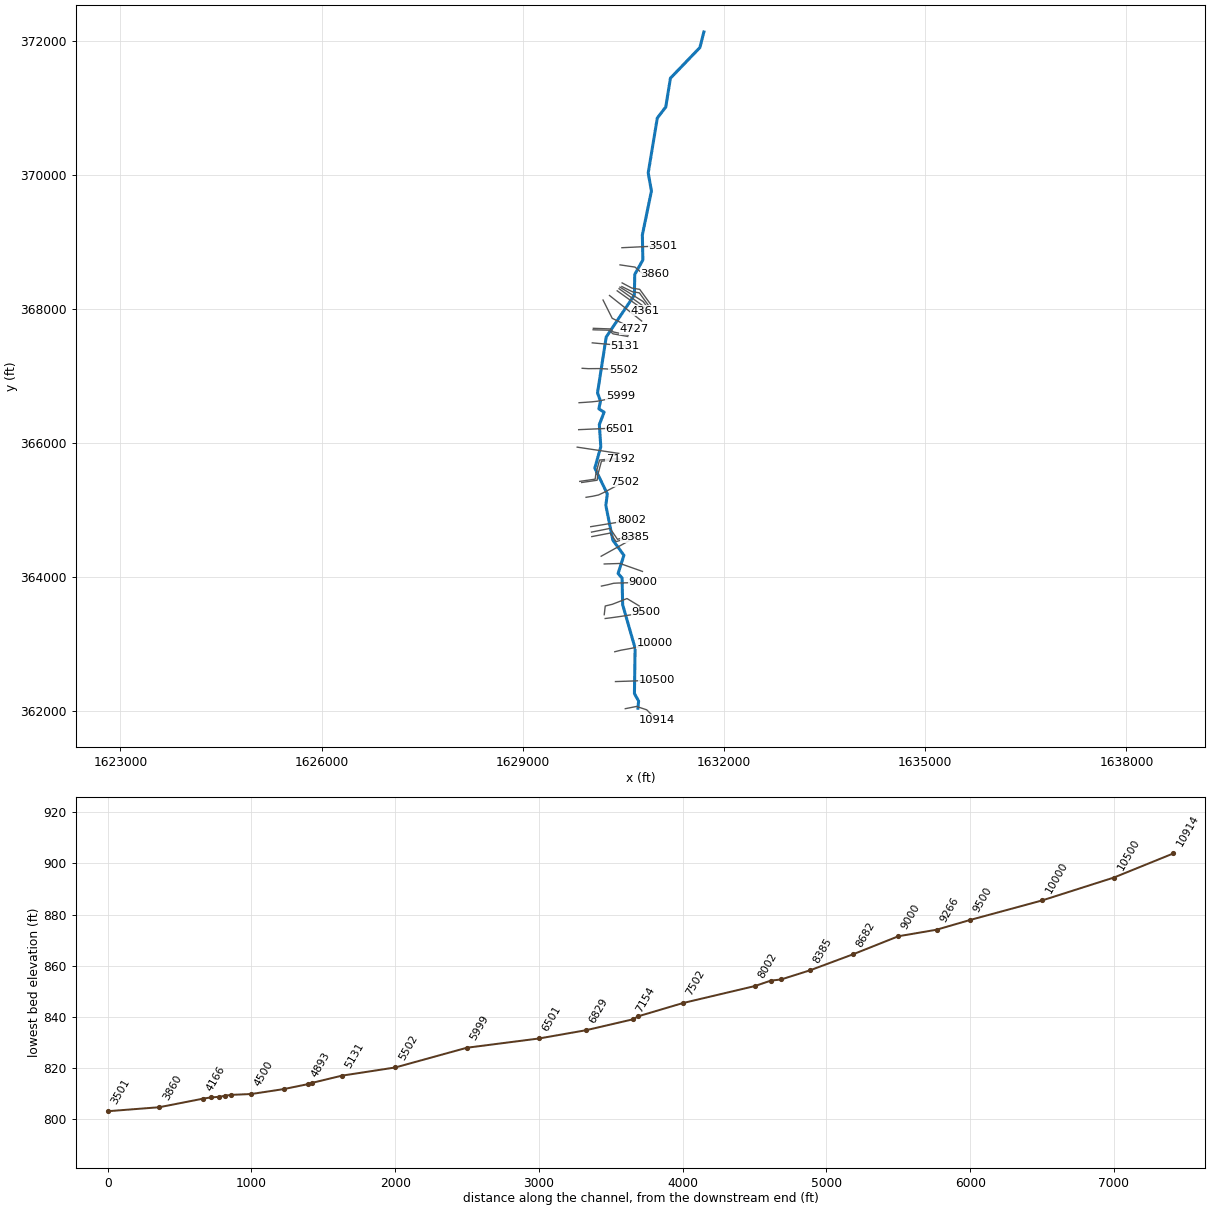
--- FLUHRTYFK.prj (project) ---

Proj Title=FLUHRTYFK
Current Plan=p01
Default Exp/Contr=0,0
English Units
Geom File=g01
Flow File=f01
Plan File=p01
BEGIN DESCRIPTION:
---------- MODELED AS PART OF WVEMD CTP PROGRAM, 2023----------
Stream Name: Fluharty Fork
Flood Zone:  AFH
Wetzel County, WV
HEC-RAS Version: RAS 6.3
Vertical Datum: NAVD88
Projection: NAD 1983 StatePlane West Virginia S FIPS 4702 (US Feet)
Terrain: 1-meter West Virginia FEMA R3 South Central (collected 2018-2020)
Land Use: 2019 NLCD
Hydrologic Method:
WV 2010 Regional Regression Equations
Additional Model Notes:
None
END DESCRIPTION:
DSS Export Rating Curves= 0
DSS Export Rating Curve Sorted= 0
DSS Export Volume Flow Curves= 0
DXF OffsetX= 0
DXF OffsetY= 0
DXF ScaleX= 0
DXF ScaleY= 0

--- FLUHRTYFK.p01 (plan) ---

Plan Title=Floodplain
Program Version=6.30
Short Identifier=Floodplain
Geom File=g01
Flow File=f01
Subcritical Flow
K Sum by GR= 0
Std Step Tol= 0.01
Critical Tol= 0.01
Num of Std Step Trials= 20
Max Error Tol= 0.3
Flow Tol Ratio= 0.001
Split Flow NTrial= 30
Split Flow Tol= 0.02
Split Flow Ratio= 0.02
Log Output Level= 0
Friction Slope Method= 1
Unsteady Friction Slope Method= 2
Unsteady Bridges Friction Slope Method= 1
Parabolic Critical Depth
Global Vel Dist= 0 , 0 , 0
Global Log Level= 0
CheckData=True
Encroach Param=-1 ,0,0, 0
Mapping Interval=1HOUR
Computation Time Step Use Courant=        0
Computation Time Step Use Time Series=    0
Computation Time Step Count To Double=0
Computation Time Step Max Doubling=0
Computation Time Step Max Halving=0
Computation Time Step Residence Courant=0
Run HTab= 0
Run UNet= 0
Run Sediment= 0
Run PostProcess= 0
Run WQNet= 0
Run RASMapper= 0
UNET Theta= 0
UNET Theta Warmup= 0
UNET ZTol= 0
UNET ZSATol= 0
UNET MxIter= 0
UNET Max Iter WO Improvement= 0
UNET MaxInSteps= 0
UNET DtIC= 0
UNET DtMin= 0
UNET MaxCRTS= 0
UNET WFStab= 0
UNET SFStab= 0
UNET WFX= 1
UNET SFX= 1
UNET Gravity=32.17405
UNET 1D Methodology=Finite Difference
UNET DSS MLevel= 1
UNET Pardiso=0
UNET DZMax Abort= 0
UNET Use Existing IB Tables= 0
UNET Froude Reduction=False
UNET Froude Limit= 0
UNET Froude Power= 0
UNET D1 Cores= 0
UNET WindReference=Eulerian
UNET WindDragFormulation=Hsu (1988)
UNET D2 Coriolis=0
UNET D2 Cores= 0
UNET D2 Theta= 1
UNET D2 Theta Warmup= 1
UNET D2 Z Tol= 0.01
UNET D2 Volume Tol= 0.01
UNET D2 Max Iterations= 20
UNET D2 Equation= 0
UNET D2 RampUpFraction=0.1
UNET D2 TimeSlices= 1
UNET D2 Turbulence Formulation=Non-Conservative (original)
UNET D2 Eddy Viscosity=0.3
UNET D2 Transverse Eddy Viscosity=0.1
UNET D2 Smagorinsky Mixing=0
UNET D2 BCVolumeCheck=0
UNET D2 Cores=0
UNET D2 SolverType=PARDISO (Direct)
UNET D2 Minimum Iterations= 3
UNET D2 Maximum Iterations= 30
UNET D2 Restart Number= 10
UNET D2 Relaxation Coeff=1.3
UNET D2 SOR Precondition Iterations= 10
UNET D2 ILUT Maximum Fill= 8
UNET D2 ILUT Tolerance=1E-08
UNET D2 Convergence Tolerance=0.00001
UNET D1D2 MaxIter= 0
UNET D1D2 ZTol=0.01
UNET D1D2 QTol=0.1
UNET D1D2 MinQTol=1
Write IC File= 0
Write IC File at Fixed DateTime=0
Write IC File at Sim End=0
Echo Input=False
Echo Parameters=False
Echo Output=False
Write Detailed= 0
HDF Write Warmup=0
HDF Write Time Slices=0
HDF Flush=0
HDF Compression= 1
HDF Chunk Size= 1
HDF Spatial Parts= 1
HDF Use Max Rows=0
HDF Fixed Rows= 1
Calibration Method= 0
Calibration Iterations= 20
Calibration Max Change=0.05
Calibration Tolerance=0.2
Calibration Maximum=1.5
Calibration Minimum=0.5
Calibration Optimization Method= 1
WQ AD Non Conservative
WQ ULTIMATE=-1
WQ Max Comp Step=1HOUR
WQ Output Interval=15MIN
WQ Output Selected Increments= 0
WQ Output face flow=0
WQ Output face velocity=0
WQ Output face area=0
WQ Output face dispersion=0
WQ Output cell volume=0
WQ Output cell surface area=0
WQ Output cell continuity=0
WQ Output cumulative cell continuity=0
WQ Output face conc=0
WQ Output face dconc_dx=0
WQ Output face courant=0
WQ Output face peclet=0
WQ Output face adv mass=0
WQ Output face disp mass=0
WQ Output cell mass=0
WQ Output cell source sink temp=0
WQ Output nsm pathways=0
WQ Output nsm derived pathways=0
WQ Create Restart=0
WQ Fixed Restart=0
WQ System Summary=0
WQ Write To DSS=0
Sorting and Armoring Iterations= 10
XS Update Threshold= 0.02
Bed Roughness Predictor= 0
Hydraulics Update Threshold= 0.02
Energy Slope Method= 1
Volume Change Method= 1
Sediment Retention Method= 0
Sediment TS Multiplier= 1
Warm Up Method= 0
XS Weighting Method= 0
Number of US Weighted Cross Sections= 1
Number of DS Weighted Cross Sections= 1
Upstream XS Weight=0
Main XS Weight=1
Downstream XS Weight=0
Number of DS XS's Weighted with US Boundary= 1
Upstream Boundary Weight= 1
Weight of XSs Associated with US Boundary= 0
Number of US XS's Weighted with DS Boundary= 1
Downstream Boundary Weight= 0.5
Weight of XSs Associated with DS Boundary= 0.5
Percentile Method= 0
Sediment Output Level= 3
Mass or Volume Output= 0
Output Increment Type= 1
Profile and TS Output Increment= 1
Transport Output Increment 1
XS Output Flag= 0
XS Output Increment= 10
Read HDF5 Sediment Hotstart= 0
Sediment Hotstart Type= 0
Write Gradation File= 0
Read Gradation Hotstart= 0
Write HDF5 File= 1
Write Binary Output= 1
Write DSS Sediment File= 0
DSS Sediment Output Type= 1
SV Curve= 0
Specific Gage Flag= 0
Subcell Erosion Methods= 0
Subcell Deposition Methods= 0
Advection Scheme= 1
Matrix Solver= 0
Implicit Weighting Factor= 1
Maximum Outer Loop Convergence Iterations= 5
Convergence Maximum Absolute= 0.001
Convergence RMSE= 0.0001
Grain Fractions Max Abs Error= 0.001
Max Subgrid Regions= 1
Max Subgrid Length Scale= 3.402823E+38
Initial Layer Thickness= 3.402823E+38
Min Layer Thickness= 3.402823E+38
Max Layer Thickness= 3.402823E+38
Number of Layers= 5

--- FLUHRTYFK.f01 (steady flow) ---

Flow Title=Flow
Program Version=4.00
Number of Profiles=1
Profile Names=F01pct
River Rch & RM=FLUHRTYFK,Main,10914
     665
River Rch & RM=FLUHRTYFK,Main,9266
     747
River Rch & RM=FLUHRTYFK,Main,7192
    1070
River Rch & RM=FLUHRTYFK,Main,4919
    1590
Boundary for River Rch & Prof#=FLUHRTYFK,Main      ,1
Up Type=0
Dn Type=3
Dn Slope=0.007292

--- FLUHRTYFK.g01 (geometry) ---

Geom Title=Geometry
Program Version=6.31

River Reach=FLUHRTYFK       ,Main
Reach XY= 30
     1630716.393      362046.385     1630727.007      362151.995
     1630664.384      362263.442     1630674.468      362941.147
     1630488.722      363589.133     1630480.231      363987.159
1630420.45981641364054.483975303     1630507.628      364325.448
     1630341.784      364552.654     1630238.132      365070.088
1630260.09036335365241.040121117     1630073.714      365625.433
     1630162.872      365944.385     1630141.113      366275.012
     1630212.375      366459.526     1630133.577      366509.114
     1630158.371      366623.236     1630114.217      366747.887
     1630243.283      367580.027 1630663.5506313368205.947307246
      1630669.12      368512.523     1630790.077      368729.705
     1630782.735      369102.625     1630918.014      369757.552
     1630869.709      370026.855     1631005.568      370845.031
     1631131.163       371009.27     1631201.206       371439.19
     1631640.642      371896.234     1631699.939      372128.677

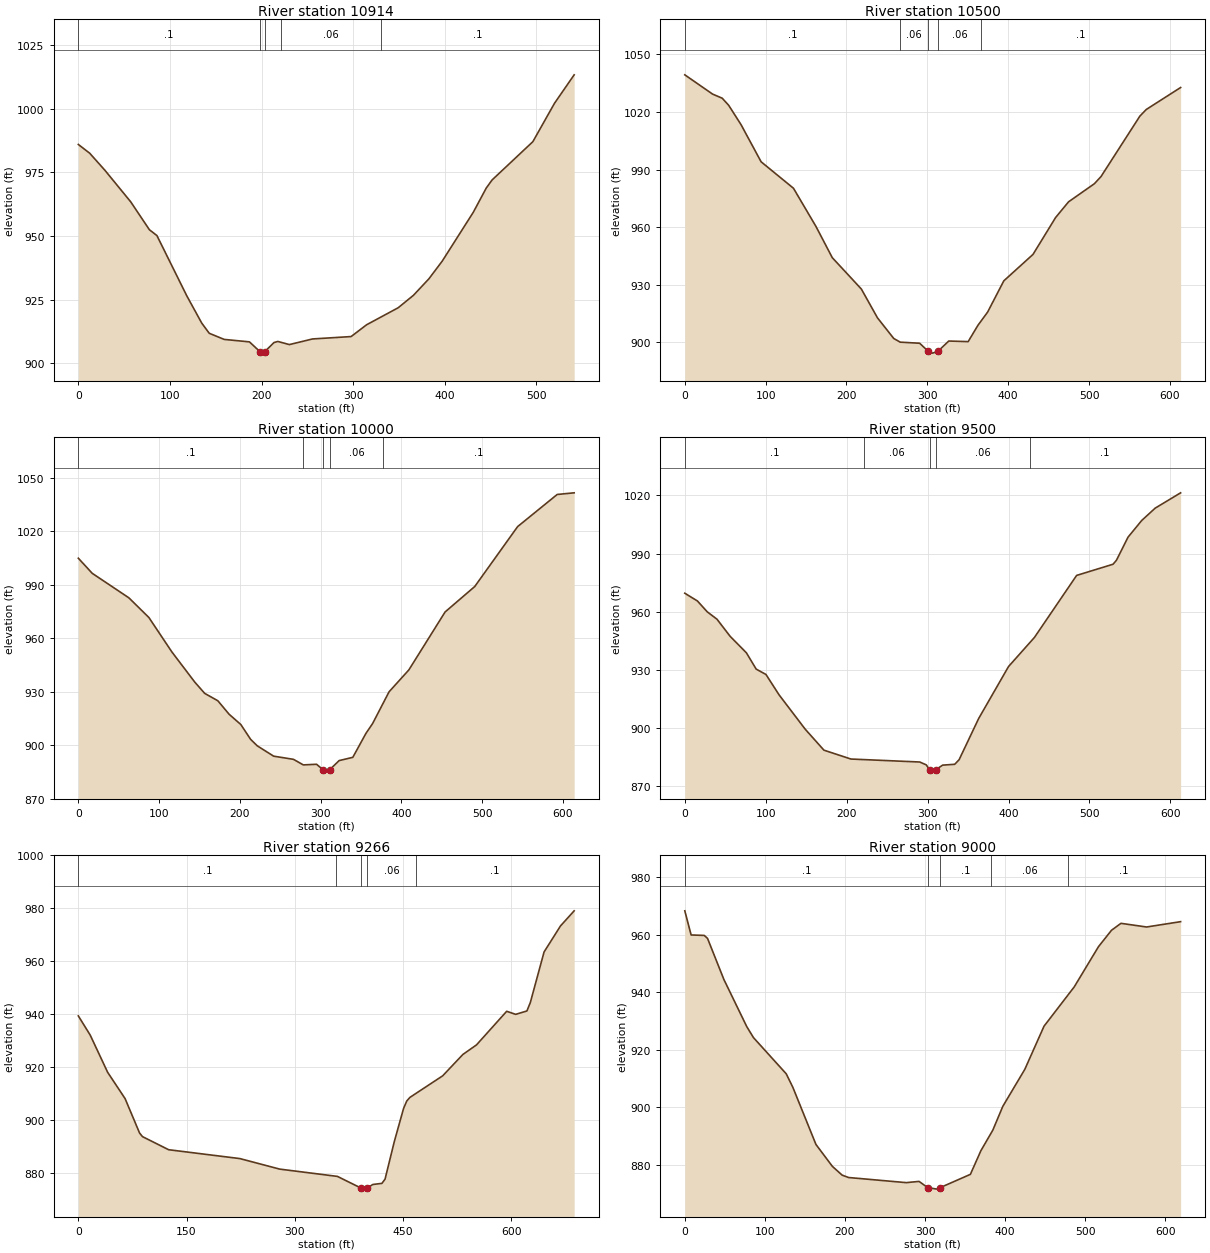
Type RM Length L Ch R = 1 ,10914   ,412.9,414.4,414
XS GIS Cut Line= 4
1630527.96457392 362038.731920541630695.75563399362072.033962997
1630846.89567283362022.0808993121630996.75486389361873.502556043
#Sta/Elev= 30
       0  986.03    12.4  982.59    28.9  975.92    57.2  963.45    77.6  952.47
    85.8  950.17   118.4  926.46   134.7  915.74   142.9  911.72   159.2   909.3
   186.8  908.33   198.3904.4844   200.9   903.9   203.5904.4761   213.6  908.06
   217.8   908.5   230.4  907.26   255.7  909.48   297.8  910.42   314.7  915.06
   349.2  921.76   365.8  926.64   382.7  933.14   397.3  940.13   431.2  959.35
   445.3  968.85   451.7  972.06   496.2  987.12   519.9 1002.27   541.3 1013.44
#Mann= 5, -1 ,  0
       0     0.1       0   198.3   0.045       0   203.5     0.1       0
  221.06    0.06       0  330.25     0.1       0
Bank Sta=198.3,203.5
XS Rating Curve= 0 ,0
Exp/Cntr(USF)=0,0
Exp/Cntr=0.3,0.1

Type RM Length L Ch R = 1 ,10500   ,498.6,499.5,499.9
XS GIS Cut Line= 6
1630381.79487868362442.9748873411630637.78649268362451.353807583
1630737.83812983 362455.671384261630812.97643101362460.001756176
1630900.63865726362465.0735964181630994.52954559 362469.25993976
#Sta/Elev= 30
       0  1039.4    34.3 1029.38    46.3 1027.22    54.3 1023.52    69.6 1013.44
    94.4   994.1   134.4  980.34   162.4  960.32   182.4   944.2   218.4  927.83
   238.4   912.8   258.5  902.07   266.5  900.17   290.5  899.61     301895.4688
   306.5  894.46   313.2  895.44   326.5  900.76   350.5  900.45   362.6  908.95
   374.6  915.85   394.6   932.1   430.7  945.87   458.7   965.1   474.7  973.26
   506.6  982.68   514.8   986.4   562.9  1017.9   570.9 1021.38   613.3 1032.79
#Mann= 5, -1 ,  0
       0     0.1       0  266.13    0.06       0     301   0.045       0
   313.2    0.06       0  366.27     0.1       0
Bank Sta=301,313.2
XS Rating Curve= 0 ,0
Exp/Cntr(USF)=0,0
Exp/Cntr=0.3,0.1

Type RM Length L Ch R = 1 ,10000   ,499.9,500,499.7
XS GIS Cut Line= 6
1630371.40907267362887.6593654161630463.66774642362910.894555166
1630549.97892551362926.0349448321630623.66906685362940.024746254
1630721.65705983362959.9856643381630972.74973351363011.136152595
#Sta/Elev= 30
       0 1004.83    17.2  996.38    62.6  982.63    87.4   971.6   115.9  952.28
   144.3  935.34   156.5  929.08   172.8  924.93   186.7  917.39   201.2  911.64
   213.4   903.3   221.6  899.68   241.9  893.89   266.4  892.12   278.6     889
     295  889.36     303886.3113   307.2  885.51   311.3  886.32     323  891.42
   339.9  893.24   356.2   906.7   364.4  912.16   384.8  929.97   409.3  942.23
   454.2  974.72   490.9  988.97     544 1022.55     593 1040.56     614 1041.48
#Mann= 5, -1 ,  0
       0     0.1       0  277.77    0.06       0     303   0.045       0
   311.3    0.06       0  377.78     0.1       0
Bank Sta=303,311.3
XS Rating Curve= 0 ,0
Exp/Cntr(USF)=0,0
Exp/Cntr=0.3,0.1

Type RM Length L Ch R = 1 ,9500    ,232.8,234,234.6
XS GIS Cut Line= 6
1630228.62425326363383.1495161651630321.63456592363395.156053841
1630408.36667593363406.8620671781630482.54106826363417.967688009
1630581.34861343363433.3659511661630834.54233275 363472.82486175
#Sta/Elev= 30
       0  969.57    15.6  965.58    27.7     960    39.8  956.17      56  947.37
    76.1  938.87    88.2  930.47   100.3  927.69   116.5  917.19   148.8  899.49
   171.9  888.69   205.3  884.12   290.3  882.59   298.4   881.1   302.4  878.56
   306.5  877.89   309.9 878.576   318.6  880.98   333.5  881.41   338.9  883.76
   363.1  905.02     400   931.8     432  946.79   484.1  978.74   529.1  984.51
   533.3  986.56   547.6  998.45   564.6 1007.09   581.2 1013.42   612.6 1021.31
#Mann= 5, -1 ,  0
       0     0.1       0   221.3    0.06       0   302.4   0.045       0
   309.9    0.06       0   426.3     0.1       0
Bank Sta=302.4,309.9
XS Rating Curve= 0 ,0
Exp/Cntr(USF)=0,0
Exp/Cntr=0.3,0.1

Type RM Length L Ch R = 1 ,9266    ,267.3,266,264.9
XS GIS Cut Line= 5
1630214.18883898363440.1908554511630229.21358763 363569.69352736
 1630333.6643527363594.8062261491630553.47241596363680.851612634
1630736.12710843363570.670766783
#Sta/Elev= 30
       0  939.41    16.5  932.15    40.6  918.15    64.8  908.22    84.9  895.22
    88.9  893.88   125.2  888.93   223.9  885.59   279.1  881.62   359.1  878.87
   391.9 874.456   395.1  874.07   400.7874.4868     408  875.81   420.8  876.25
   425.1  877.83     438  892.07   450.8  904.53   455.2   907.3   459.5  908.66
     505  916.81     533  924.87   551.8  928.46   593.7  941.15   606.1  939.99
   621.7  941.27   626.4  944.39   645.5  963.52   668.3  973.35   687.2  979.04
#Mann= 5, -1 ,  0
       0     0.1       0   357.8    0.06       0   391.9   0.045       0
   400.7    0.06       0   467.8     0.1       0
Bank Sta=391.9,400.7
XS Rating Curve= 0 ,0
Exp/Cntr(USF)=0,0
Exp/Cntr=0.3,0.1

Type RM Length L Ch R = 1 ,9000    ,320.3,318.2,316.5
XS GIS Cut Line= 6
  1630172.367476363866.7223679271630269.03362125363887.242996171
 1630355.5662566363908.7252366691630430.49163167363912.704231337
1630605.43944451363916.9722674191630786.55620825363925.491607338
#Sta/Elev= 30
       0  968.38     7.9  959.98    24.3  959.82    28.4  958.79    48.8   944.5
    77.4  928.07    85.8  924.24   126.7  911.65     135  906.93   163.8  887.07
   184.4  879.41   196.5  876.39   204.6  875.55   276.6  873.77   292.6   874.2
   303.5  872.01   315.2  871.51   318.9872.0267   356.7  876.65   369.9  884.93
   384.7  892.02   397.2  900.32   424.7  913.21   448.7  928.23   486.4   941.9
   516.7   955.9     533  961.62   544.8  964.03   576.8  962.75   619.3  964.61
#Mann= 5, -1 ,  0
       0     0.1       0   303.5   0.045       0   318.9     0.1       0
  383.01    0.06       0  478.01     0.1       0
Bank Sta=303.5,318.9
XS Rating Curve= 0 ,0
Exp/Cntr(USF)=0,0
Exp/Cntr=0.3,0.1

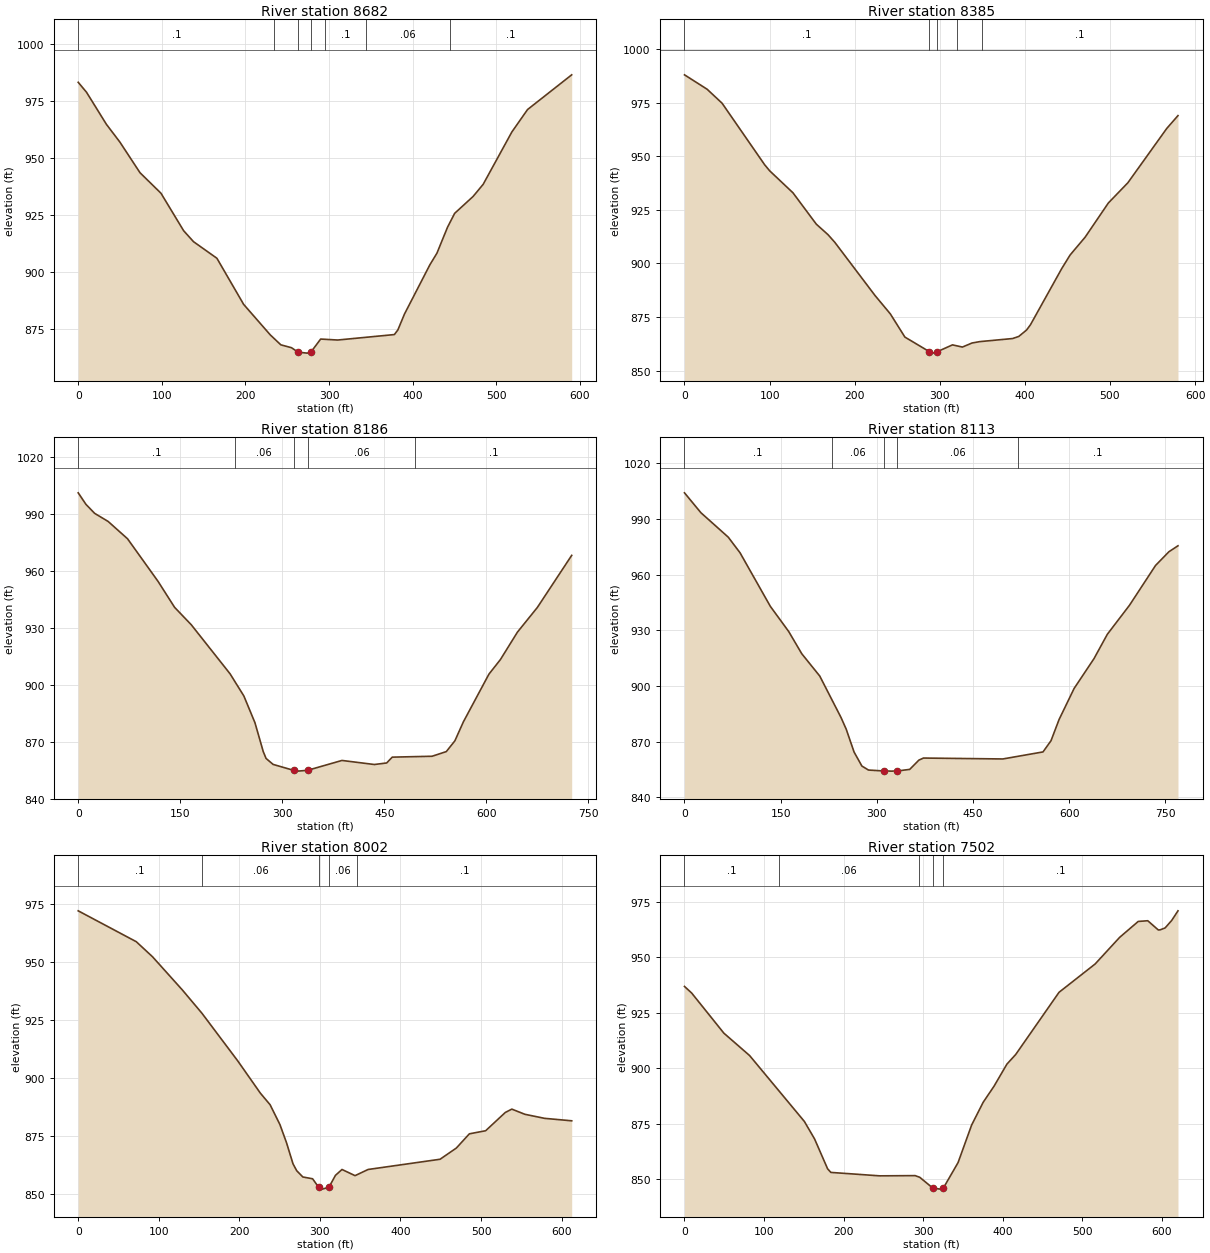
Type RM Length L Ch R = 1 ,8682    ,286.7,296.9,298.9
XS GIS Cut Line= 3
1630214.30067783364196.2526592331630448.84427319364203.840834377
1630784.10364775364085.189368485
#Sta/Elev= 30
       0   983.3     9.9  978.95    33.8  964.81    49.8  957.08    73.9  943.61
      99  934.59   126.1  918.14   137.9  913.33   165.9  906.04   197.9  885.79
   229.9  872.34   242.4  868.03   255.1  866.77   263.1864.8022     274  864.39
   278.4864.8582     290  870.57   310.3  870.14   378.2  872.54   382.4  874.59
   390.2  881.49   420.6  903.13   429.1  908.27   441.8  919.69   450.3  925.76
   472.4  933.19   484.4   938.5   518.7  961.47   537.5  971.34   590.3  986.58
#Mann= 7, -1 ,  0
       0     0.1       0  234.67    0.06       0   263.1   0.045       0
   278.4    0.06       0  294.67     0.1       0  344.67    0.06       0
  444.67     0.1       0
Bank Sta=263.1,278.4
XS Rating Curve= 0 ,0
Exp/Cntr(USF)=0,0
Exp/Cntr=0.3,0.1

Type RM Length L Ch R = 1 ,8385    ,209.9,199.7,187.3
XS GIS Cut Line= 2
1630168.66560917364311.8438033261630675.68181799364593.389670436
#Sta/Elev= 30
       0  987.97    26.6  981.25    44.2  974.72    94.2  946.03   100.1  943.21
   127.5  932.94   154.9  918.33   168.7  913.41   176.6  909.88   223.9  885.06
   241.9  876.48     259  865.67   287.6  858.91   292.2  858.19   297.3858.9075
   314.9  862.04   326.6  861.02   337.9  862.91   347.1  863.56   385.5  864.99
   392.8  865.97     402  868.97   406.6  871.45   443.2  897.55   453.1  903.93
   470.8  912.26   498.1  928.21     521  937.62   566.7  962.95   579.9  968.94
#Mann= 5, -1 ,  0
       0     0.1       0   287.6   0.045       0   297.3     0.1       0
     320    0.06       0     350     0.1       0
Bank Sta=287.6,297.3
XS Rating Curve= 0 ,0
Exp/Cntr(USF)=0,0
Exp/Cntr=0.3,0.1

Type RM Length L Ch R = 1 ,8186    ,75.8,72.5,75.6
XS GIS Cut Line= 4
1630028.91640286364604.5623153221630304.76428013364657.272100787
1630390.85692972364529.0116228221630668.46179984364613.347279566
#Sta/Elev= 30
       0 1001.33    11.4  995.24    24.2   990.5      44  986.24    72.5  977.12
   117.3  954.69   141.7  940.97   166.2  931.79   223.2  905.95   243.5  894.26
   259.8  880.16     272  864.94   276.1  861.34   286.5  858.18   316.6855.0619
   322.7  854.64   337.1  855.06   387.7  860.27   435.3  858.13   453.4  858.94
   461.6  862.01   520.2  862.48   541.1  864.94   553.7  870.62   566.2  880.62
   603.8  905.79   620.6  913.43   645.7  927.93   674.9   940.9   725.4  968.37
#Mann= 5, -1 ,  0
       0     0.1       0     230    0.06       0   316.6   0.045       0
   337.1    0.06       0  495.31     0.1       0
Bank Sta=316.6,337.1
XS Rating Curve= 0 ,0
Exp/Cntr(USF)=0,0
Exp/Cntr=0.3,0.1

Type RM Length L Ch R = 1 ,8113    ,97.9,110.8,117.4
XS GIS Cut Line= 4
1630024.81460099 364671.497037251630301.34317328 364726.92960283
1630411.94084391364563.2729833741630689.54571402364647.608640118
#Sta/Elev= 30
       0 1003.99    25.6  993.28    68.3  980.11    86.7  971.68   133.9  942.87
   162.5  929.35   182.9  917.38     211  905.34   244.1  883.06   252.2  876.79
   264.5  864.45   276.7   856.9     287  854.75   310.9854.2505   323.2  854.17
   331.8  854.25   351.3  855.11   365.6  860.09   372.7  861.21   496.5  860.72
   559.2  864.51   571.7  870.56   584.2  881.91   607.7  898.67   638.6  914.66
   659.5  927.82   694.1  943.47   734.7  964.88   755.6  972.28   769.7  975.48
#Mann= 5, -1 ,  0
       0     0.1       0     230    0.06       0   310.9   0.045       0
   331.8    0.06       0  519.55     0.1       0
Bank Sta=310.9,331.8
XS Rating Curve= 0 ,0
Exp/Cntr(USF)=0,0
Exp/Cntr=0.3,0.1

Type RM Length L Ch R = 1 ,8002    ,498,500.7,502.4
XS GIS Cut Line= 6
1630012.98885776364752.2524210071630105.51360708 364767.35967426
1630265.89025484364793.543677002 1630438.6034921 364821.74211143
1630524.95994668364835.8414926681630617.48502409 364850.94776167
#Sta/Elev= 30
       0  972.17    72.1  958.84    92.3  952.32   129.4  937.96   153.6  927.95
   198.1  907.36   226.1  893.47   238.2  888.46   250.4  879.89   258.5  872.13
   266.6  862.98   271.2     860   278.8  857.29   290.9  856.52   298.4852.8705
   303.1  852.05   311.2  852.87   319.3     858   327.4  860.53   343.6  857.87
   359.8  860.53   449.1  864.94   469.3  869.77   485.5  875.92   505.7  877.25
   530.1  885.14   538.2  886.58   554.4  884.35   578.7  882.61   612.5  881.54
#Mann= 5, -1 ,  0
       0     0.1       0  153.75    0.06       0   298.4   0.045       0
   311.2    0.06       0  346.25     0.1       0
Bank Sta=298.4,311.2
XS Rating Curve= 0 ,0
Exp/Cntr(USF)=0,0
Exp/Cntr=0.3,0.1

Type RM Length L Ch R = 1 ,7502    ,304.6,309.2,312.8
XS GIS Cut Line= 6
1629943.22128075365190.3732639251630040.32476109365206.055647254
1630129.05096158365225.1517376751630197.35528693365257.093274832
1630286.28588334365302.8385901751630511.89205943365424.227783084
#Sta/Elev= 30
       0  936.82       9  933.86    49.5  915.76    81.9  905.65   150.8  875.92
   163.6  868.05     180  854.57   184.1  852.94   245.5  851.39   290.1  851.49
   295.9  850.74   312.3845.8874   321.6   845.4   325.6  845.89   344.1  857.37
   361.2  874.34   375.7  884.58   389.3   891.8   405.5  901.77   416.6  906.13
   471.1  934.18   516.5  946.95   547.3  958.95   570.7  966.14   582.7  966.46
     596  962.29   598.3  962.35   604.5  963.21   612.9  966.63   620.7  970.93
#Mann= 5, -1 ,  0
       0     0.1       0  118.36    0.06       0  294.52     0.1       0
   312.3   0.045       0   325.6     0.1       0
Bank Sta=312.3,325.6
XS Rating Curve= 0 ,0
Exp/Cntr(USF)=0,0
Exp/Cntr=0.3,0.1

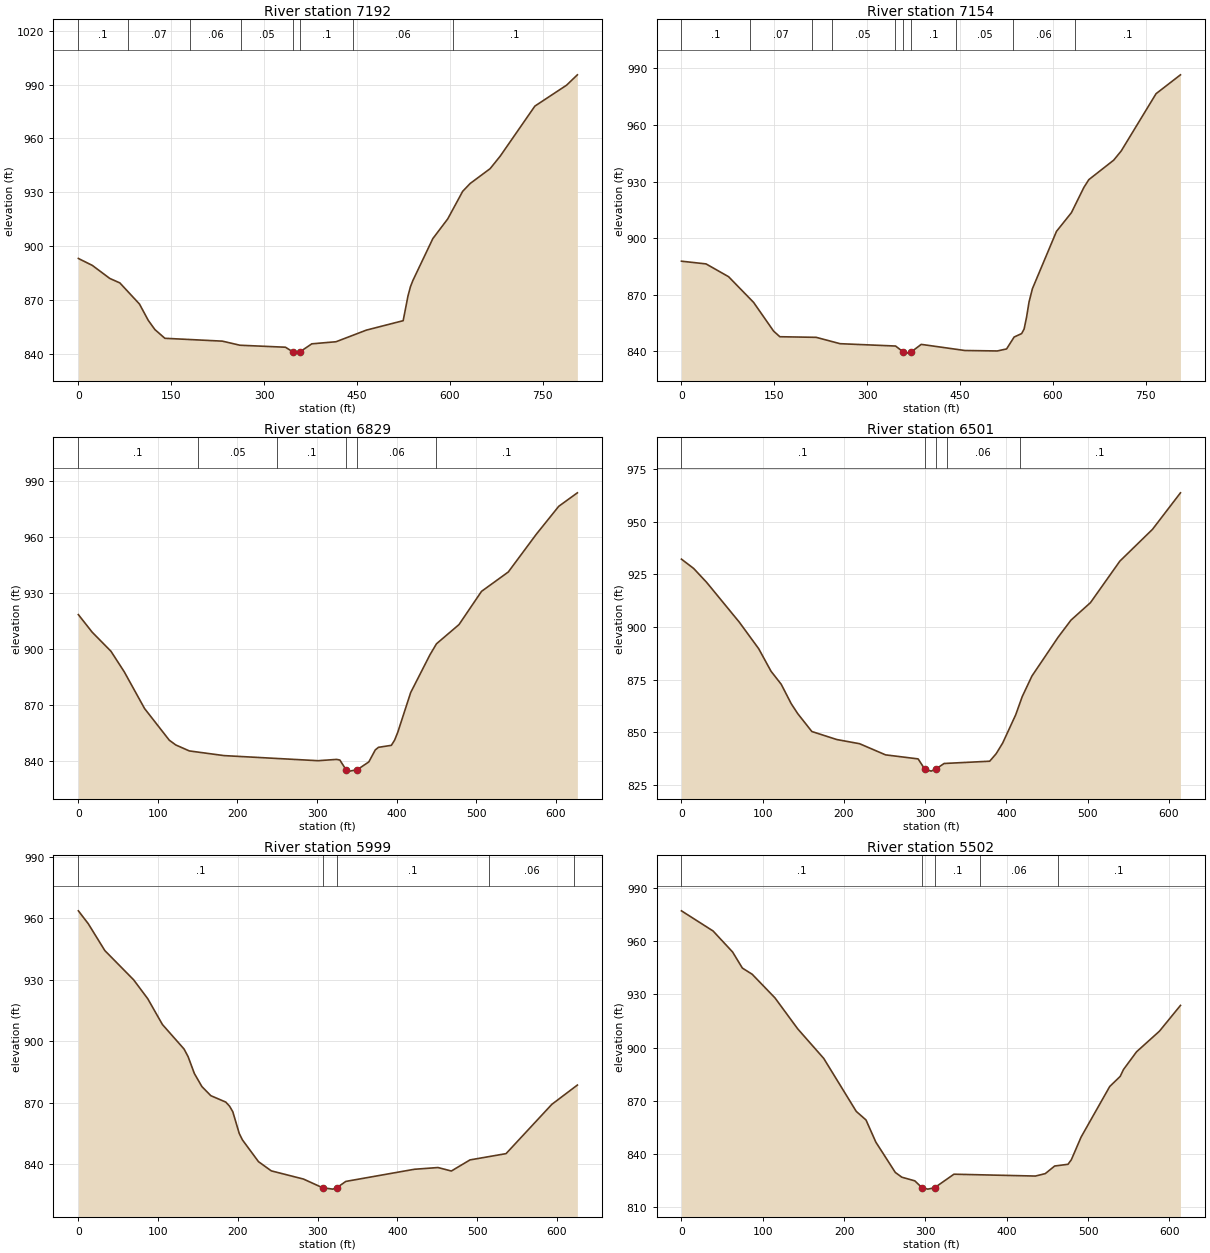
Type RM Length L Ch R = 1 ,7192    ,38.2,38.1,39
XS GIS Cut Line= 5
1629877.81501786365411.0220329351630107.98108106365444.404897063
1630118.52303815365525.2265681091630172.98981646365729.037738574
1630452.35167943365757.149624155
#Sta/Elev= 30
       0  893.03    22.5  889.17    50.8  881.88      67   879.4    98.7  867.61
   112.8  858.56   123.6  853.38   139.7  848.52   232.6  846.93   260.9  844.65
   334.4  843.54   346.5  840.93   351.2  840.25   357.8840.9519   376.9  845.43
   416.1   846.6   465.1  853.08   524.5  858.34   532.2     872   536.2  877.22
   540.2  880.76   572.4   904.1   596.5  915.11   620.6  930.46   632.7  934.83
   664.9  943.09     681  949.98   737.2  977.98   788.4  989.64   805.8  995.41
#Mann= 8, -1 ,  0
       0     0.1       0      80    0.07       0     180    0.06       0
  262.57    0.05       0   346.5   0.045       0   357.8     0.1       0
  444.08    0.06       0  605.04     0.1       0
Bank Sta=346.5,357.8
XS Rating Curve= 0 ,0
Exp/Cntr(USF)=0,0
Exp/Cntr=0.3,0.1

Type RM Length L Ch R = 1 ,7154    ,331.5,325.3,315.5
XS GIS Cut Line= 5
1629848.82463586365427.7134649991630078.99069905365461.096329127
1630089.53265615365541.9180001731630143.99943446365745.729170638
1630423.36129742365773.841056219
#Sta/Elev= 30
       0  887.78    39.7  886.34    76.1  879.56   116.5  865.94   148.8  850.72
   158.9  847.74   217.5  847.42   256.2  844.05   345.8  842.81   358.2  839.65
   364.1  839.05   371.1 839.707   387.2  843.69   457.6  840.44     510   840.2
     525  841.27   537.2  847.58   549.3   849.4   553.3  851.81   557.3  858.12
   561.3   866.2   566.7  873.17   605.6  903.59   629.7  913.49   649.8  926.86
   657.8  930.99     698  941.34   710.1  946.19   766.4  976.56   805.8  986.56
#Mann= 10, -1 ,  0
       0     0.1       0     110    0.07       0     210    0.06       0
  242.57    0.05       0  344.08     0.1       0   358.2   0.045       0
   371.1     0.1       0  444.08    0.05       0  535.04    0.06       0
  635.04     0.1       0
Bank Sta=358.2,371.1
XS Rating Curve= 0 ,0
Exp/Cntr(USF)=0,0
Exp/Cntr=0.3,0.1

Type RM Length L Ch R = 1 ,6829    ,326.4,328.3,329.2
XS GIS Cut Line= 2
1629811.04928961365938.1198875851630431.26776524365844.999266597
#Sta/Elev= 30
       0  918.59    17.3  909.21      41  898.95    57.7  887.95    83.2  868.32
   114.3  851.35   122.4  848.82   139.5  845.61   183.1  843.11   301.3  840.38
   324.7  841.08   328.7  840.72   336.4  835.57   340.8   834.8   350.6835.5708
   365.1  839.74   373.2  846.16   377.2  847.54   393.4  848.61   397.5   851.4
   401.5  855.66   417.7  876.88   441.9  897.07   450.1  902.96   478.4  913.24
   506.7  931.02   540.4  941.41   575.4  961.51   603.8  976.57   627.2  983.78
#Mann= 6, -1 ,  0
       0     0.1       0     150    0.05       0     250     0.1       0
   336.4   0.045       0   350.6    0.06       0     450     0.1       0
Bank Sta=336.4,350.6
XS Rating Curve= 0 ,0
Exp/Cntr(USF)=0,0
Exp/Cntr=0.3,0.1

Type RM Length L Ch R = 1 ,6501    ,494,501.5,499.8
XS GIS Cut Line= 6
1629833.10732776366198.8761681771630014.18636192366206.749512002
1630189.02131408366214.3518590031630263.95029809366217.609726503
1630351.47997868366218.8331492541630446.26981534366207.759352505
#Sta/Elev= 30
       0  932.29      15  927.88      31  921.26    71.1   902.4    95.1  889.72
   110.2  879.06   122.8  872.83   135.1  863.61   143.1  858.89   160.5  850.38
   191.2  846.57   219.2  844.59   251.2  839.29   291.3  837.37   299.3  832.61
   307.3  831.56   313.3832.5954   323.3  835.19   379.4  836.27   387.4  839.86
   395.4  844.93   411.4  858.32   419.4  866.95   431.4  876.76   463.4  895.08
   479.4   903.3   503.4  911.61   539.6  931.35   579.8  946.47   614.2  963.81
#Mann= 5, -1 ,  0
       0     0.1       0   299.3   0.045       0   313.3     0.1       0
  326.25    0.06       0  416.25     0.1       0
Bank Sta=299.3,313.3
XS Rating Curve= 0 ,0
Exp/Cntr(USF)=0,0
Exp/Cntr=0.3,0.1

Type RM Length L Ch R = 1 ,5999    ,499.3,497.1,495.4
XS GIS Cut Line= 6
1629838.97050501366600.5207060871629936.92765817366606.907832429
1630028.83101767366613.7657583361630106.96242309366622.002946585
1630205.49798718366641.4294169251630455.27406242366698.666179091
#Sta/Elev= 30
       0  963.66    12.4  957.38    33.2  944.27    69.3  930.01      87  920.79
   105.4  908.21   132.5  896.26   137.5  892.62   145.5  884.27   154.9  877.94
   166.1   873.5   184.8  870.39   189.6  868.37   193.6  865.69   201.7  855.08
   205.7  851.95   225.8  841.34   241.9  836.84   282.3  832.84   306.1  828.62
     319  827.94   324.1828.6475   335.3   831.7   421.2  837.62   450.9  838.47
   467.6  836.77     491  842.19   536.2  845.25   593.6  869.29   625.6  878.69
#Mann= 5, -1 ,  0
       0     0.1       0   306.1   0.045       0   324.1     0.1       0
  514.32    0.06       0  621.82     0.1       0
Bank Sta=306.1,324.1
XS Rating Curve= 0 ,0
Exp/Cntr(USF)=0,0
Exp/Cntr=0.3,0.1

Type RM Length L Ch R = 1 ,5502    ,371.8,371.4,371.3
XS GIS Cut Line= 6
1629885.31260392367113.8297188431629979.53255984367108.192591012
1630067.32372284367109.1538751721630142.57390042367109.528874427
1630242.49627276367104.6771780851630497.99116859367085.023017928
#Sta/Elev= 30
       0  977.12    38.9  965.75    62.9  953.91    74.9  944.85      87  941.36
     115  928.05     143  910.58     175  893.91     215  864.05     227  859.21
     239  846.79     263  829.65     271  826.97     287  824.91   295.9     821
     303  820.24   311.3821.0068   335.1  828.65   435.3  827.61   447.4  828.98
     459  833.27   475.4  834.24   479.5  836.81   491.5  849.59   526.7  878.09
   539.6   883.8   543.6  887.65   559.7  897.66   587.8  909.25   613.7   923.8
#Mann= 5, -1 ,  0
       0     0.1       0   295.9   0.045       0   311.3     0.1       0
  367.48    0.06       0  462.48     0.1       0
Bank Sta=295.9,311.3
XS Rating Curve= 0 ,0
Exp/Cntr(USF)=0,0
Exp/Cntr=0.3,0.1

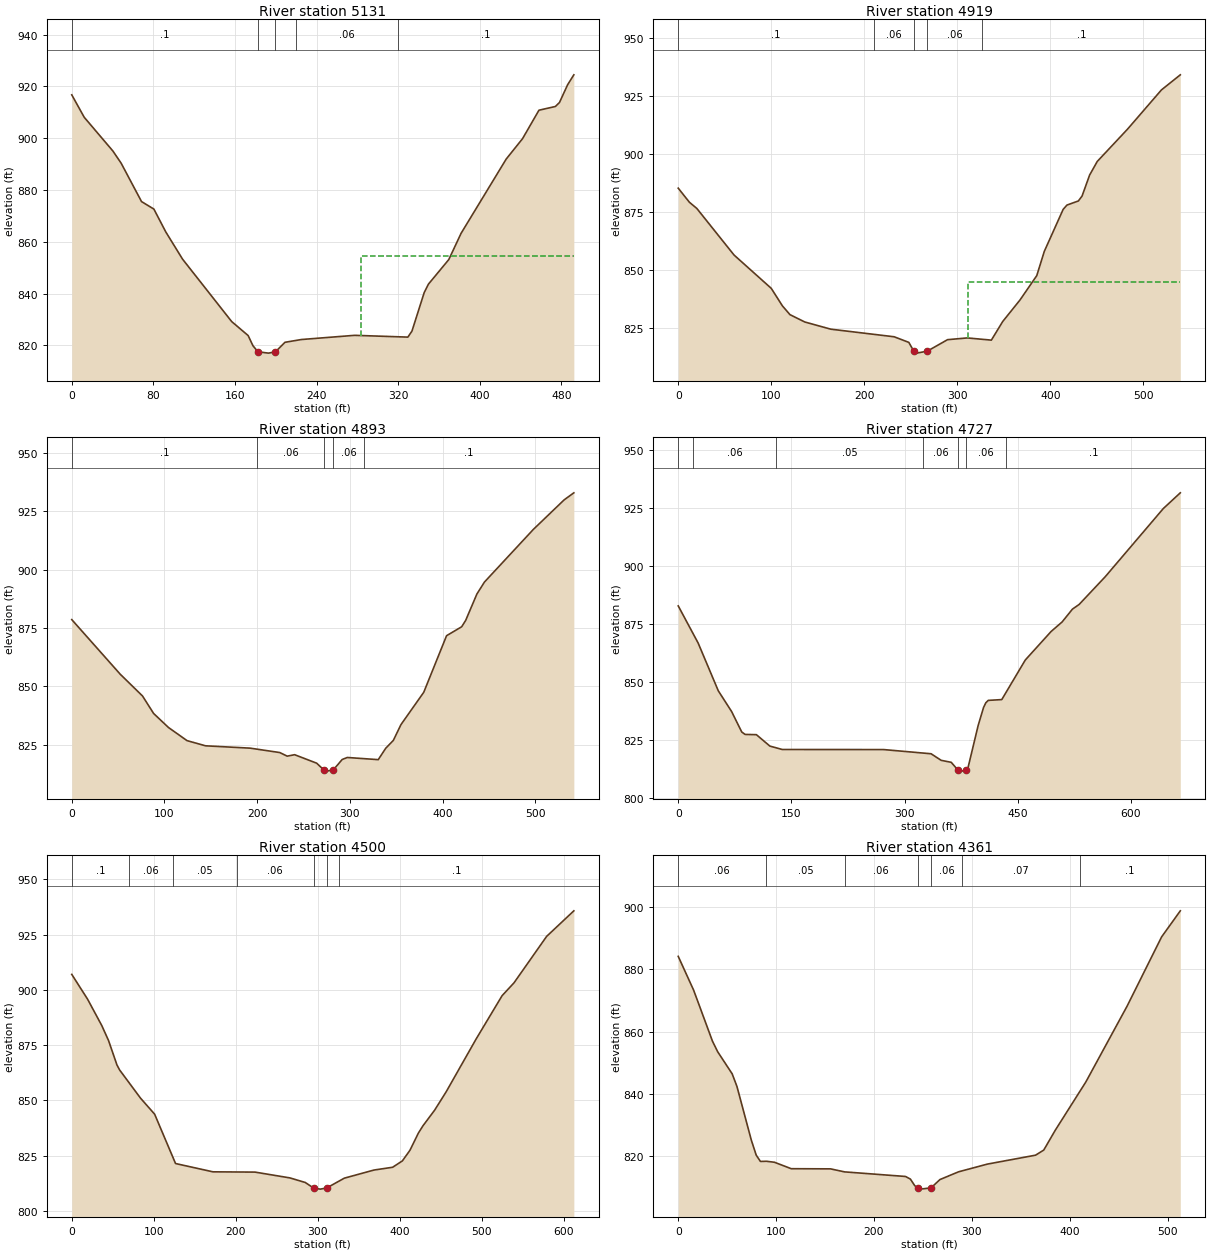
Type RM Length L Ch R = 1 ,5131    ,214.8,211.3,205
BEGIN DESCRIPTION:
Structure XS 4
END DESCRIPTION:
XS GIS Cut Line= 2
1630035.94437426  367493.05855881630526.14537908367449.133737579
#Sta/Elev= 30
       0  916.73    12.2  908.08    40.3  895.06    48.4  890.36    68.4  875.53
    80.5  872.64    92.2   863.8   108.6  853.32   156.8  829.21   172.9  823.83
   177.6  819.91   182.5817.5573   192.9  817.04   199.7  817.56     209  821.22
   225.1  822.29   277.3  823.91   329.5  823.22   333.5  825.54   345.5  840.41
   349.6  843.64   369.6  853.15   381.7  863.31   425.9  891.95   441.9  899.81
     458   910.8   474.1  912.24   478.1  913.77   486.1  920.63   492.2  924.46
#Mann= 5, -1 ,  0
       0     0.1       0   182.5   0.045       0   199.7     0.1       0
     220    0.06       0     320     0.1       0
#XS Ineff= 2 , 0
                          283.28          854.61
Permanent Ineff=
       F       F
Bank Sta=182.5,199.7
XS Rating Curve= 0 ,0
Exp/Cntr(USF)=0,0
Exp/Cntr=0.3,0.1

Type RM Length L Ch R = 1 ,4919    ,26.7,26.5,25.8
BEGIN DESCRIPTION:
Structure XS 3
END DESCRIPTION:
XS GIS Cut Line= 4
1630048.10503705367687.8843343411630282.78659924367681.675827405
 1630344.8716686 367627.661817061630564.03196345367588.548223362
#Sta/Elev= 30
       0  885.37      12   879.3      20  876.61      60  856.51     100  842.13
     112  834.56   120.1  830.78   136.1   827.6   164.1   824.5   232.1  821.23
   247.9   818.8   253.1815.0886   256.4  814.17   267.7  815.02   289.5  819.98
   310.8  820.73   336.6  819.78   348.8  827.82   367.4  837.12   385.4  847.62
   393.5  858.09   413.8  876.24   417.9  878.09   430.1  879.84   434.1  881.97
   442.2  891.02   450.4  896.89   482.9  910.81   519.4  927.77   539.7  934.29
#Mann= 5, -1 ,  0
       0     0.1       0     210    0.06       0   253.1   0.045       0
   267.7    0.06       0  327.06     0.1       0
#XS Ineff= 2 , 0
                          311.55          844.68
Permanent Ineff=
       F       F
Bank Sta=253.1,267.7
XS Rating Curve= 0 ,0
Exp/Cntr(USF)=0,0
Exp/Cntr=0.3,0.1

Type RM Length L Ch R = 1 ,4893    ,163.9,166.4,168
BEGIN DESCRIPTION:
Structure XS 2
END DESCRIPTION:
XS GIS Cut Line= 4
1630051.89183136367710.0951691761630302.09466089367700.782408772
1630349.27931361367656.0811588311630570.30216054367607.654804729
#Sta/Elev= 30
       0  878.65    52.3  855.24    76.3  845.92    88.3  838.42   104.3  832.42
   124.3  826.79   144.3  824.56   192.4  823.56   224.4  821.67   232.4  820.13
   240.4  820.75   264.2  817.11   271.8  814.26   275.2  813.71   282.2 814.285
   291.7  818.69   297.2  819.56   330.6  818.63   338.7  823.52   346.9  826.89
   355.1  833.64   379.7  847.51   404.3  871.75   420.6  875.59   424.9   878.3
     437   889.6   445.2  894.76     498  917.34   531.2  929.99   541.6  932.99
#Mann= 5, -1 ,  0
       0     0.1       0     200    0.06       0   271.8   0.045       0
   282.2    0.06       0  315.37     0.1       0
Bank Sta=271.8,282.2
XS Rating Curve= 0 ,0
Exp/Cntr(USF)=0,0
Exp/Cntr=0.3,0.1

Type RM Length L Ch R = 1 ,4727    ,227.9,226.6,224.8
XS GIS Cut Line= 3
1630196.28774995 368131.821320011630332.99184444367859.272905206
1630656.26693582367699.354907876
#Sta/Elev= 30
       0  882.98    26.4  866.98    53.1   846.4    70.8  837.45    84.2  828.65
    88.7   827.6   103.6   827.5   121.5  822.58   137.9  821.11   272.2  821.08
   335.2  819.27   348.6  816.44   361.9  815.59   371.3812.0727   375.3  811.79
   380.9  812.07   384.3  813.44   397.6  831.45   404.8  839.25   407.8  841.25
     411  842.27   428.9  842.61   460.1  859.67   494.4  871.98   508.9  876.06
   522.6  881.59   531.5  883.61   566.1  895.56   643.1  924.94   665.6   931.7
#Mann= 7, -1 ,  0
       0    0.05       0      20    0.06       0     130    0.05       0
  324.91    0.06       0   371.3   0.045       0   380.9    0.06       0
  434.91     0.1       0
Bank Sta=371.3,380.9
XS Rating Curve= 0 ,0
Exp/Cntr(USF)=0,0
Exp/Cntr=0.3,0.1

Type RM Length L Ch R = 1 ,4500    ,137.9,138.4,138.6
XS GIS Cut Line= 6
1630292.98107992368199.3393588361630366.39694358368141.037310094
 1630493.6525946368039.9817379271630630.69661184367931.151903093
1630699.21944067367876.7376418411630772.63563243367818.435921177
#Sta/Elev= 30
       0  907.02    19.3   895.8    36.7  883.81    44.9  877.06    55.1  866.07
    58.3  863.82    83.9  851.01   101.1  843.77   126.6  821.44   172.2  817.69
   223.6  817.56   266.1  814.94   284.9  812.86   295.1  810.34   303.2  809.86
     311  810.38   332.5  814.82   368.6  818.49   391.4  819.75   403.3  822.63
   412.6  827.46   422.8  835.18   428.4   838.5   442.7   845.6   456.9     854
   493.3  877.79     525   897.4   539.5   903.2   579.3  924.21   612.5  935.78
#Mann= 7, -1 ,  0
       0     0.1       0      70    0.06       0  123.75    0.05       0
  201.25    0.06       0   295.1   0.045       0     311    0.06       0
  326.25     0.1       0
Bank Sta=295.1,311
XS Rating Curve= 0 ,0
Exp/Cntr(USF)=0,0
Exp/Cntr=0.3,0.1

Type RM Length L Ch R = 1 ,4361    ,41.7,41.7,41.8
XS GIS Cut Line= 2
1630407.36157585 368268.950457071630824.31598305367970.092962893
#Sta/Elev= 30
       0  884.19    15.7  873.38      35  856.98    40.3   853.6    55.1  846.52
      60  842.46    74.7  825.22    79.7  820.41      84  818.41      90  818.47
    98.3  818.15   115.5  816.08   155.6  816.03     170  815.06   232.2  813.59
   237.2  812.75   241.6  810.67   244.5  809.92   247.4  809.53   258.3809.9325
   267.4   812.6   286.4  815.08   315.9  817.56   365.1  820.42   373.5  822.07
   385.2   828.4   416.5  843.92   458.6  868.21   493.9  890.44     513   898.8
#Mann= 7, -1 ,  0
       0    0.06       0      90    0.05       0     170    0.06       0
   244.5   0.045       0   258.3    0.06       0     290    0.07       0
     410     0.1       0
Bank Sta=244.5,258.3
XS Rating Curve= 0 ,0
Exp/Cntr(USF)=0,0
Exp/Cntr=0.3,0.1

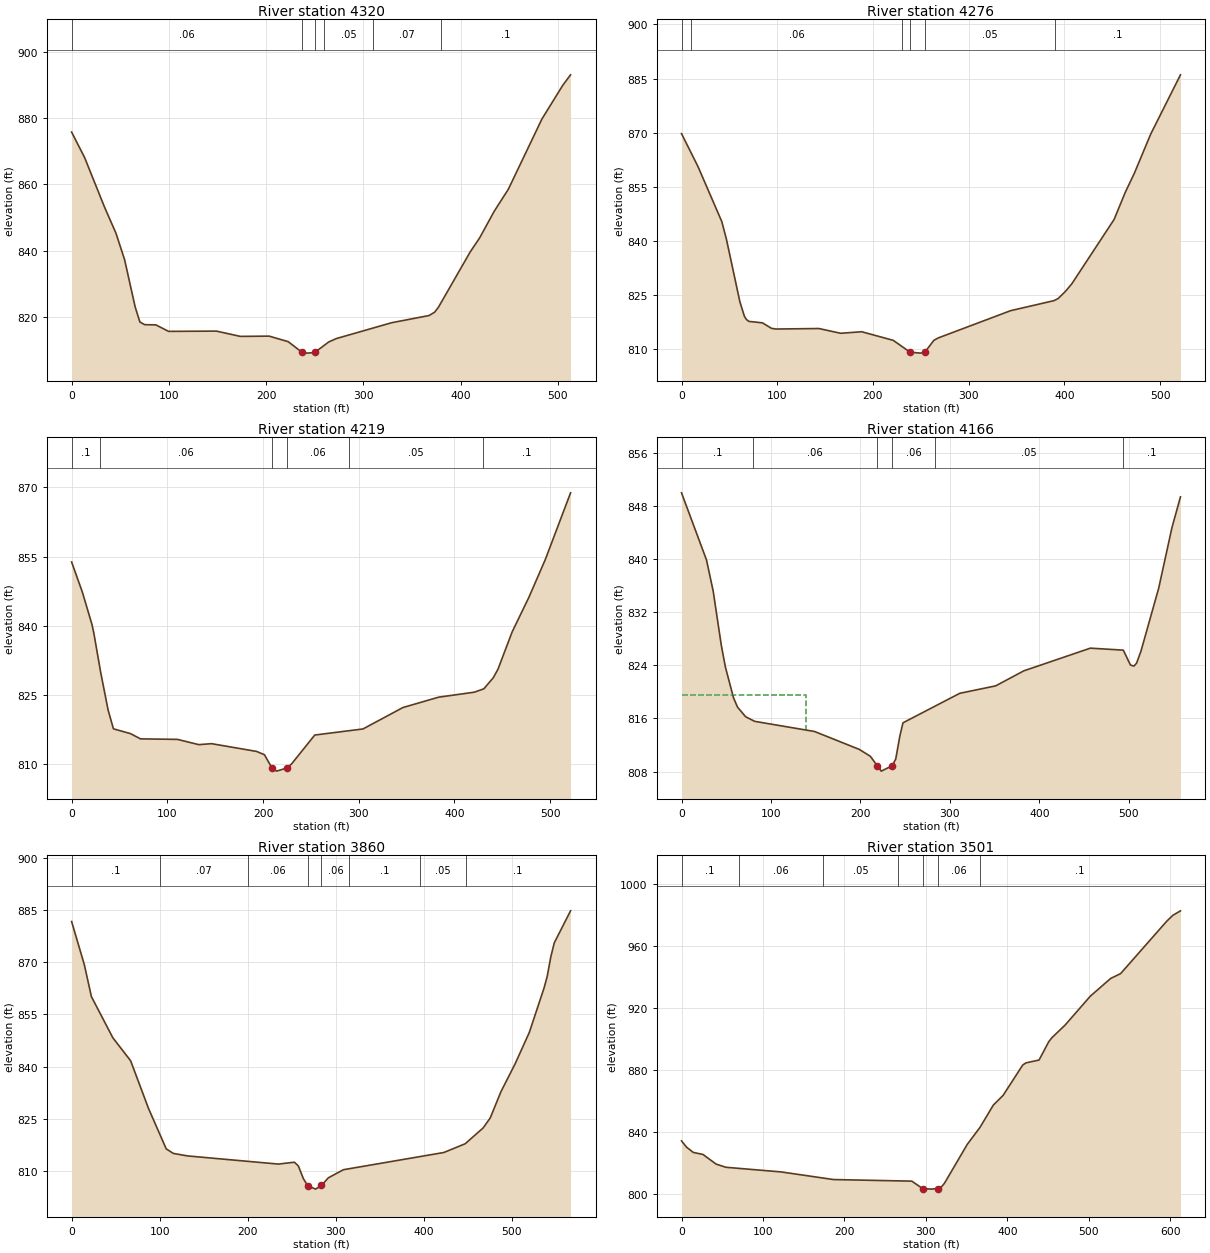
Type RM Length L Ch R = 1 ,4320    ,42.9,43.5,43.9
XS GIS Cut Line= 2
1630435.07819829368300.2822911371630852.03260549 368001.42479696
#Sta/Elev= 30
       0  875.77    13.3  868.15    33.9  853.14    45.6  845.32    54.5  837.33
    65.3  823.17    70.2  818.58    75.1  817.78    86.6  817.72    99.7  815.76
   148.9  815.84   173.5  814.25   203.1  814.33   222.7  812.66   237.1809.4147
   242.4  809.21     250  809.41   264.3  812.56     272  813.58   329.1  818.37
   367.5  820.53   373.2  821.52   377.2  823.05   409.7  839.63   419.6  843.95
   434.4  851.87   449.1   858.6   483.6  879.73   505.1  889.91     513  893.01
#Mann= 6, -1 ,  0
       0    0.06       0   237.1   0.045       0     250    0.06       0
     260    0.05       0     310    0.07       0     380     0.1       0
Bank Sta=237.1,250
XS Rating Curve= 0 ,0
Exp/Cntr(USF)=0,0
Exp/Cntr=0.3,0.1

Type RM Length L Ch R = 1 ,4276    ,54.5,57.8,60.6
XS GIS Cut Line= 3
1630448.33397425368324.3837019571630792.98414898368109.881145653
1630862.87824036368018.295784534
#Sta/Elev= 30
       0  869.69    17.2  860.56    42.1  845.26    46.9   840.4      61  822.97
    65.7  818.98    67.8  818.09    70.4  817.56    84.5  817.16      94  815.63
    98.5  815.44   143.5  815.58   166.3  814.26   188.2  814.69   221.2   812.3
   238.7809.0153   249.5  808.75   254.2  809.01   263.6  812.31   268.3  812.98
   343.7  820.53   388.9  823.31   393.4   823.9   400.9  825.85   407.6  827.96
   451.9  845.87   463.4  853.31   473.1  858.74   490.2  869.61   521.2  886.02
#Mann= 6, -1 ,  0
       0     0.1       0      10    0.06       0     230    0.05       0
   238.7   0.045       0   254.2    0.05       0     390     0.1       0
Bank Sta=238.7,254.2
XS Rating Curve= 0 ,0
Exp/Cntr(USF)=0,0
Exp/Cntr=0.3,0.1

Type RM Length L Ch R = 1 ,4219    ,52.6,52.8,52.7
XS GIS Cut Line= 4
1630476.97389649368332.4304076681630632.53985193368255.573148907
1630737.80848338368238.444582045 1630879.4674572368043.213477819
#Sta/Elev= 30
       0  853.85    11.2  847.35    21.3  840.29    23.2  838.47    30.3  830.02
    38.1   821.8    43.7   817.7    61.5  816.66      72  815.52   110.6  815.41
   132.9  814.27   146.3  814.48   193.3   812.8   201.5  812.08   209.5809.1707
   214.1  808.53   224.6  809.18   229.8  810.08   254.1  816.35   304.5  817.67
   346.2  822.31   383.4  824.55   420.9  825.64   430.8  826.37   440.7  828.78
   445.6  830.64   460.4  838.72   477.9  846.22   495.1  854.43   521.4  868.84
#Mann= 6, -1 ,  0
       0     0.1       0      30    0.06       0   209.5   0.045       0
   224.6    0.06       0  290.17    0.05       0  430.17     0.1       0
Bank Sta=209.5,224.6
XS Rating Curve= 0 ,0
Exp/Cntr(USF)=0,0
Exp/Cntr=0.3,0.1

Type RM Length L Ch R = 1 ,4166    ,309.6,305.3,301.3
XS GIS Cut Line= 4
1630480.87087885368387.0473700911630625.47934378368309.922855465
1630743.30900093368290.656241675 1630905.0557093368068.908747258
#Sta/Elev= 30
       0  850.04    27.9  839.93    35.4  835.22    44.5  827.03      49   823.8
    58.1  819.13    62.6  817.72    71.7  816.26    81.8  815.57   148.7  814.04
   198.7  811.34   211.1   810.3   218.9808.8649   223.3  808.06   235.5  808.87
   239.5  809.89     244   813.3   247.6  815.35   311.1   819.8   351.2  820.92
   382.7  823.19   457.1  826.61   493.9  826.31   501.9  824.06   505.8  823.91
   508.7  824.34   513.7  826.18   533.5  835.68   548.3   844.8   557.8  849.43
#Mann= 6, -1 ,  0
       0     0.1       0      80    0.06       0   218.9   0.045       0
   235.5    0.06       0  283.28    0.05       0  493.28     0.1       0
#XS Ineff= 2 , 0
          139.45  819.55
Permanent Ineff=
       F       F
Bank Sta=218.9,235.5
XS Rating Curve= 0 ,0
Exp/Cntr(USF)=0,0
Exp/Cntr=0.3,0.1

Type RM Length L Ch R = 1 ,3860    ,352,359.6,364.8
XS GIS Cut Line= 4
1630449.78246904368655.8142528591630672.92056084368622.431388731
1630818.75096729368497.6848964641630966.33836659368520.525803499
#Sta/Elev= 30
       0  881.75    14.5  869.28    22.5  860.13    46.8   848.3    67.1  841.64
    87.3  827.98   107.5  816.29   115.6  814.98   131.8  814.26   234.9  811.91
   253.1  812.45   257.6  811.38   263.3  807.73   268.1805.7273   277.2   804.7
   283.9  805.75   291.6  807.94   308.8  810.29     423  815.25   447.2  817.77
   467.5   822.3   475.6  825.18   487.8  832.76   503.9  840.77   520.1  849.86
   536.9  862.71   540.4  865.99   544.4  871.51   548.4  875.62   566.9  884.83
#Mann= 8, -1 ,  0
       0     0.1       0     100    0.07       0     200    0.06       0
   268.1   0.045       0   283.9    0.06       0  315.62     0.1       0
  395.62    0.05       0  447.53     0.1       0
Bank Sta=268.1,283.9
XS Rating Curve= 0 ,0
Exp/Cntr(USF)=0,0
Exp/Cntr=0.3,0.1

Type RM Length L Ch R = 1 ,3501    ,499.1,499.8,498.6
XS GIS Cut Line= 6
1630477.72349259368911.6486297551630571.36766225368916.107610345
1630733.68361059368923.8365975021630833.57054992368928.593149677
1630908.48575443368932.1600716711631089.53033984368940.781445503
#Sta/Elev= 30
       0  834.27     6.4  830.13    14.4  826.85    26.4  825.51    42.4  819.31
    54.5  817.24   122.5  814.23   186.6  809.31   282.7  808.29   295.9  803.53
   306.7  803.13     315803.5309   318.8  804.41   322.8  806.94   350.8  832.05
   366.3  842.93   382.8  857.42   394.8  863.69   418.9   883.3   422.9  884.68
   438.9   886.5   450.9  898.41   454.9  901.04   470.9  909.09   501.9  927.78
   526.8  939.18     539   942.3   595.6  976.13   603.1  979.94   612.5  982.86
#Mann= 7, -1 ,  0
       0     0.1       0      70    0.06       0  173.75    0.05       0
  266.25    0.06       0   295.9   0.045       0     315    0.06       0
  366.25     0.1       0
Bank Sta=295.9,315
XS Rating Curve= 0 ,0
Exp/Cntr(USF)=0,0
Exp/Cntr=0.3,0.1