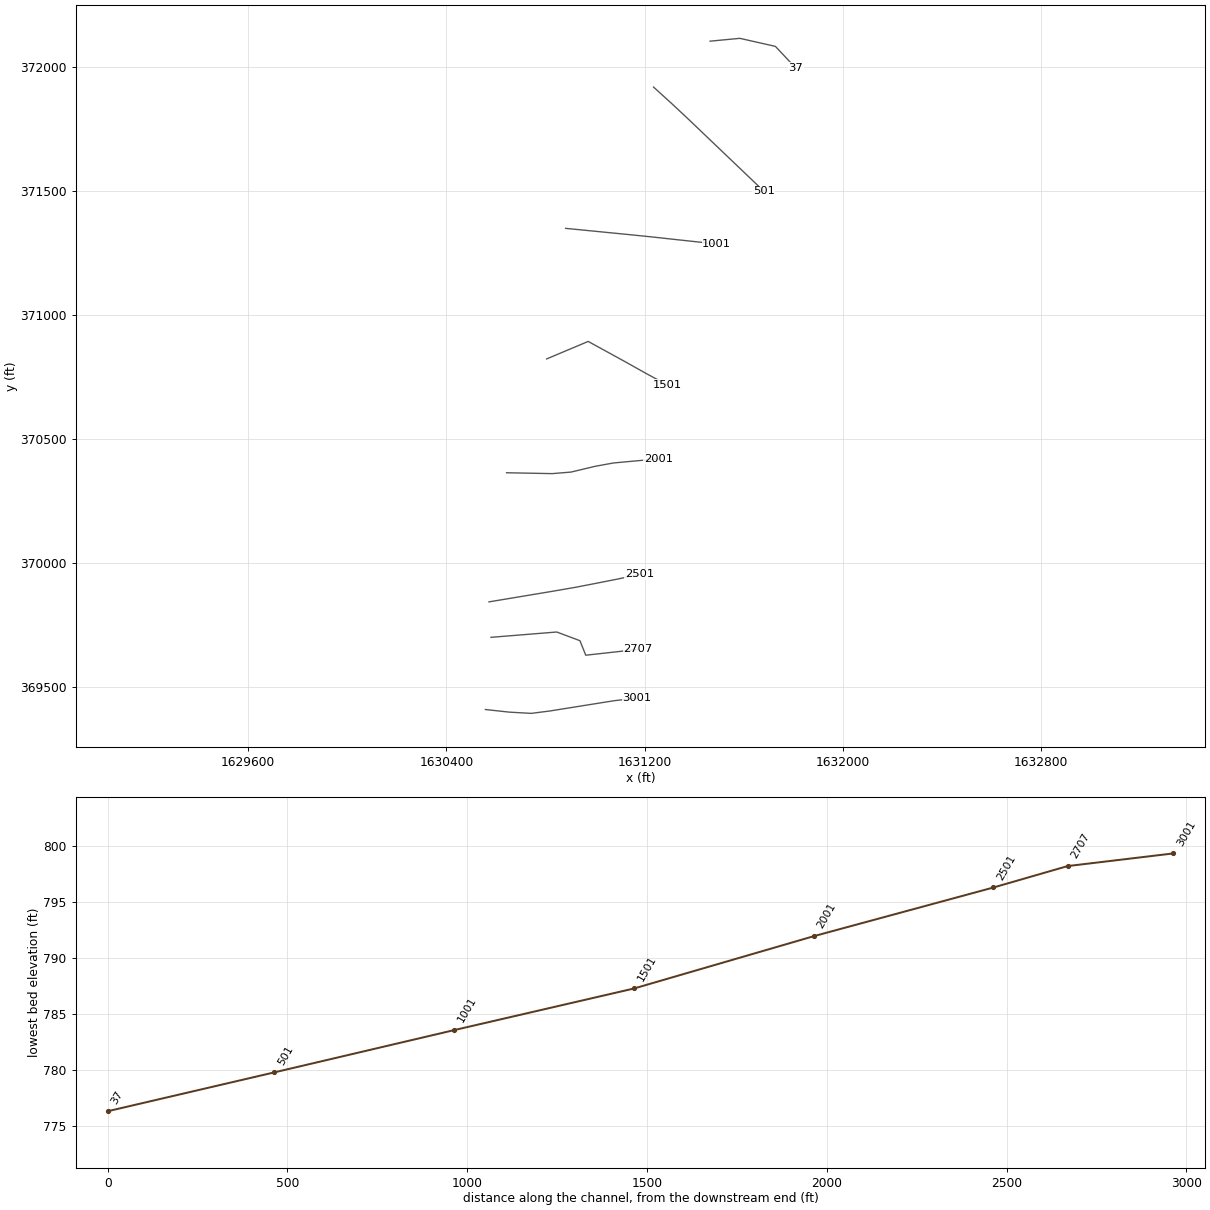
HEC-RAS study FLUHRTYFK.prj: FLUHRTYFK

--- FLUHRTYFK.g01 (geometry) --- (continued)

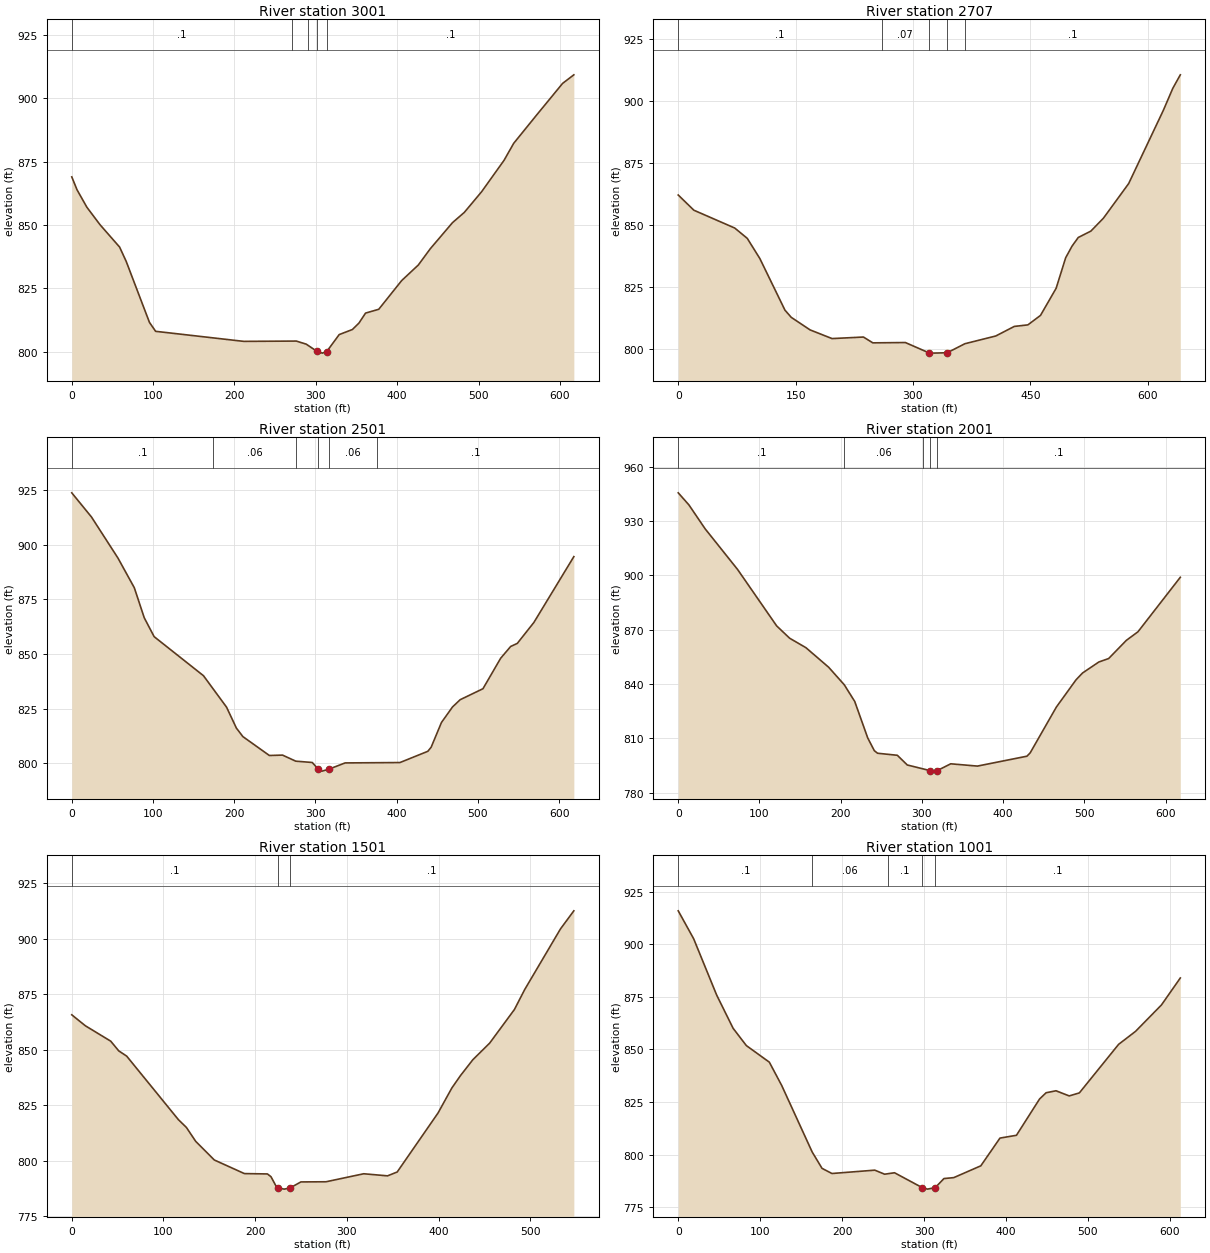
Type RM Length L Ch R = 1 ,3001    ,299.2,294.3,291.1
XS GIS Cut Line= 6
1630557.62687609369407.4068245891630653.50332476369396.920953169
1630742.10452551369391.8402546791630816.52301183369401.275275171
1631075.97065568369442.7486174261631169.42683358369453.772217423
#Sta/Elev= 30
       0  868.96     6.5  863.84    18.6  856.96    34.7  850.08    58.8  841.24
    66.9  835.59    95.5  811.49   103.1  807.97   211.4     804     276  804.12
   288.2   802.9   301.6800.0137     308  799.36   313.4 799.992   328.7  806.68
   344.9  808.68     353  811.23   361.1  815.17   377.3  816.67   405.6  828.05
   425.9  834.14   440.7   840.6     468   850.9   482.5  854.94   503.7  863.08
   531.2  875.44   543.2  882.22   571.5  893.44   603.3  905.88   617.1  909.26
#Mann= 5, -1 ,  0
       0     0.1       0  270.21    0.06       0  290.21     0.1       0
   301.6   0.045       0   313.4     0.1       0
Bank Sta=301.6,313.4
XS Rating Curve= 0 ,0
Exp/Cntr(USF)=0,0
Exp/Cntr=0.3,0.1

Type RM Length L Ch R = 1 ,2707    ,199.4,206.2,211.9
XS GIS Cut Line= 5
1630580.19151339369698.8654995491630845.69265499 369720.33985659
1630939.39894026369685.1999996131630962.82551158369626.633571319
1631173.66465344369650.060142637
#Sta/Elev= 30
       0  862.12      20  855.98    72.2  848.78    88.2  844.62   104.3  836.46
   136.4   815.6   144.4   812.7   168.5  807.62   196.6  804.11   236.7  804.73
   248.7  802.38   290.3  802.51   320.2  798.38   324.5  798.23   343.7798.3817
   366.4  802.03   405.9  805.16   429.5  809.02   446.9  809.65     463  813.47
     483  824.44   495.2  836.78   503.3  841.45   511.3  844.97   527.4  847.54
   543.5  852.78   575.7  866.75     620  896.33   632.1  905.23   641.7  910.69
#Mann= 5, -1 ,  0
       0     0.1       0     260    0.07       0   320.2   0.045       0
   343.7    0.06       0  366.37     0.1       0
Bank Sta=320.2,343.7
XS Rating Curve= 0 ,0
Exp/Cntr(USF)=0,0
Exp/Cntr=0.3,0.1

Type RM Length L Ch R = 1 ,2501    ,498.7,499.4,497.7
XS GIS Cut Line= 6
1630572.13012792369842.000771672   1630824.89373369884.126343593
1630923.43290301369901.1699446741630997.72934234369915.600690082
1631085.71473068369932.9136475921631180.19518475369952.765642002
#Sta/Elev= 30
       0  923.81    24.3  912.72    56.8  893.97      77  880.34    89.2  866.61
   101.4  857.93   162.2  840.02   190.6  825.62   202.7  816.03   210.7  812.13
   243.3  803.48   259.5  803.66   275.8  800.88   296.1  800.28   303.6 797.189
   308.2  796.32   316.3  797.17   336.6  800.08   404.1  800.25   438.4   805.4
   442.5  807.27   455.2  818.61   468.8  825.71   478.2  829.03   506.3  834.07
   528.1  848.03   540.4  853.42   548.6  854.84     569  864.43   618.2  894.58
#Mann= 6, -1 ,  0
       0     0.1       0  173.75    0.06       0  276.25     0.1       0
   303.6   0.045       0   316.3    0.06       0  376.25     0.1       0
Bank Sta=303.6,316.3
XS Rating Curve= 0 ,0
Exp/Cntr(USF)=0,0
Exp/Cntr=0.3,0.1

Type RM Length L Ch R = 1 ,2001    ,503.8,500.4,495.6
XS GIS Cut Line= 6
  1630643.039763370363.2451360081630827.51970901370359.750064254
1630903.59796892370366.0584505951631001.22671068370389.403548256
1631075.05333467370402.8080490081631256.02639793370419.484196752
#Sta/Elev= 30
       0  945.64    13.1     939    33.1  925.78    73.1  903.31   121.2  872.15
   137.2  865.35   157.2  860.14   185.2  849.33   204.4  839.67   217.3  830.43
   233.3  810.28   241.4  803.28   245.4  801.85   269.7  800.73     282  795.37
   309.6 792.313   314.9  791.98     319  792.31   335.5  796.02   368.3  794.76
   429.3  800.22   433.3  802.08   465.5  827.34   489.7  842.38   497.7  846.15
   517.8  852.23   529.9  854.15   551.7  864.19     566  868.93   618.1  899.01
#Mann= 5, -1 ,  0
       0     0.1       0  204.56    0.06       0   300.9     0.1       0
   309.6   0.045       0     319     0.1       0
Bank Sta=309.6,319
XS Rating Curve= 0 ,0
Exp/Cntr(USF)=0,0
Exp/Cntr=0.3,0.1

Type RM Length L Ch R = 1 ,1501    ,496.5,499.8,502.3
XS GIS Cut Line= 6
1630804.93970627370822.7886356371630972.62637417 370893.45798634
1631060.30795734370845.375077263 1631126.5447015370808.902381167
1631206.04027742370764.3863940841631292.79699367370717.370412007
#Sta/Elev= 30
       0  865.71    14.8  860.79    42.5  853.85    51.2   849.5    59.9  847.12
   116.3  818.54     125  815.05   135.1  808.81   155.4  800.42   188.2   794.3
   213.3  794.14   217.2  792.89   222.4  788.91   225.3 787.833   231.6  787.31
   237.9787.8146   249.8  790.55   277.2  790.62   318.3  794.22   344.3  793.28
   354.8  795.01   399.3  821.53   414.4   832.8   423.8  838.37   437.3  845.52
   455.6  852.97   482.6  868.09   493.9  877.13   532.9  904.39   547.4  912.48
#Mann= 3, -1 ,  0
       0     0.1       0   225.3   0.045       0   237.9     0.1       0
Bank Sta=225.3,237.9
XS Rating Curve= 0 ,0
Exp/Cntr(USF)=0,0
Exp/Cntr=0.3,0.1

Type RM Length L Ch R = 1 ,1001    ,505.6,500.2,494.9
XS GIS Cut Line= 6
  1630881.413302371349.9534644191631136.30977385371324.848199666
 1631235.8515695371314.7301096771631310.51152517 371306.45683226
1631397.62782076371297.0359193381631490.98557368371287.287251174
#Sta/Elev= 30
       0  915.94    18.8  902.68    46.9  875.89      67  860.07    83.1  851.87
   111.2  843.97   126.3  832.88   163.5  801.25   175.5  793.48   187.6  791.03
   239.9  792.62   251.9   790.7     264  791.38   297.8784.3193   304.2   783.6
   313.7  784.32   324.3  788.62   336.3  789.07   369.3  794.68   392.7  807.87
   412.8   809.2     441  826.45     449  829.43   461.1  830.37   477.2  827.92
   489.6  829.36   537.5  852.45   558.1   858.6   589.8  871.19   612.8     884
#Mann= 5, -1 ,  0
       0     0.1       0   163.7    0.06       0  256.13     0.1       0
   297.8   0.045       0   313.7     0.1       0
Bank Sta=297.8,313.7
XS Rating Curve= 0 ,0
Exp/Cntr(USF)=0,0
Exp/Cntr=0.3,0.1

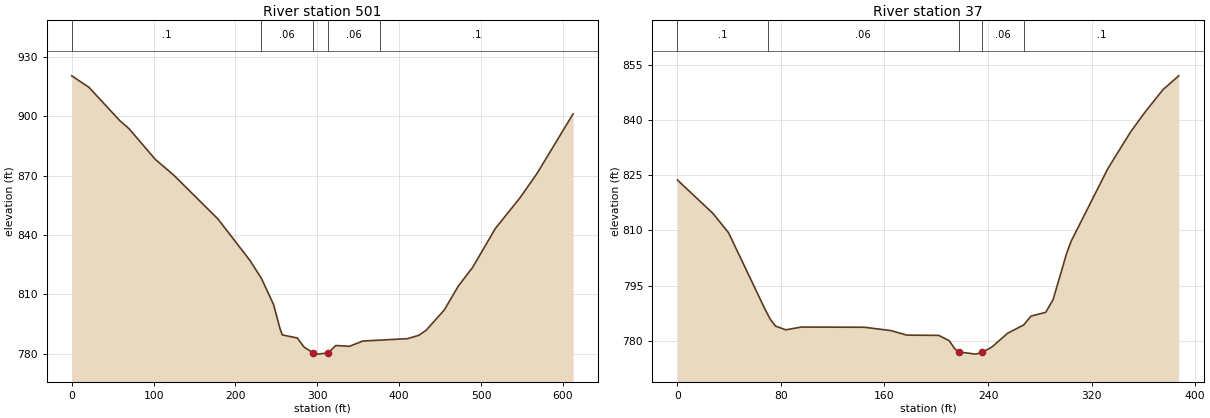
Type RM Length L Ch R = 1 ,501     ,457.6,464,467.8
XS GIS Cut Line= 6
1631236.47361551 371920.304685921631305.96068126371857.324496925
1631369.95924093371797.6464666721631550.79779001371625.027389333
 1631614.0912986371564.610515416 1631681.9057955371499.878361419
#Sta/Elev= 30
       0   920.4    21.1  914.58    59.2  897.56    69.7  893.83   102.2  878.15
   124.2  870.41   178.8  848.02   217.7  827.16   231.7  818.11   246.6  804.85
   254.3   792.9   257.2  789.54   275.6  787.97   283.8   783.4   294.9  780.45
   300.4  779.83   313.4780.4464   322.5  784.17   339.2  783.78   355.7  786.45
   409.9  787.62   424.1  789.35   433.1  791.92   455.2  802.17   472.2  814.15
   489.9  823.73   517.4  843.21   547.9  858.95   568.4  871.06   612.5  901.18
#Mann= 5, -1 ,  0
       0     0.1       0  231.29    0.06       0   294.9   0.045       0
   313.4    0.06       0  376.29     0.1       0
Bank Sta=294.9,313.4
XS Rating Curve= 0 ,0
Exp/Cntr(USF)=0,0
Exp/Cntr=0.3,0.1

Type RM Length L Ch R = 1 ,37      ,,,
XS GIS Cut Line= 4
1631464.77552174372105.6458435121631584.85985516 372117.08784216
1631728.41726045372084.6134776151631810.39151881371997.515828113
#Sta/Elev= 30
       0  823.72    27.5  814.62    39.5  809.38    67.6  788.64    71.7  785.88
    75.7  784.01    83.7  782.97    95.8  783.72   144.5  783.67     165  782.76
   177.3  781.53   201.9  781.46   210.1     780   214.1  777.91   217.2776.9609
   230.6  776.36   235.7776.8882   242.9  778.26   255.2  782.05   267.5  784.28
   273.2   786.7   284.6  787.73   290.3   791.2   300.9  803.96   304.4  807.19
   332.7  826.88   350.3  836.86   361.3  842.16   375.2   848.3   387.4  852.05
#Mann= 5, -1 ,  0
       0     0.1       0      70    0.06       0   217.2   0.045       0
   235.7    0.06       0  267.81     0.1       0
Bank Sta=217.2,235.7
XS Rating Curve= 0 ,0
Exp/Cntr(USF)=0,0
Exp/Cntr=0.3,0.1
LCMann Table=0

Chan Stop Cuts=-1
Use User Specified Reach Order=0
Composite Channel Slope=5